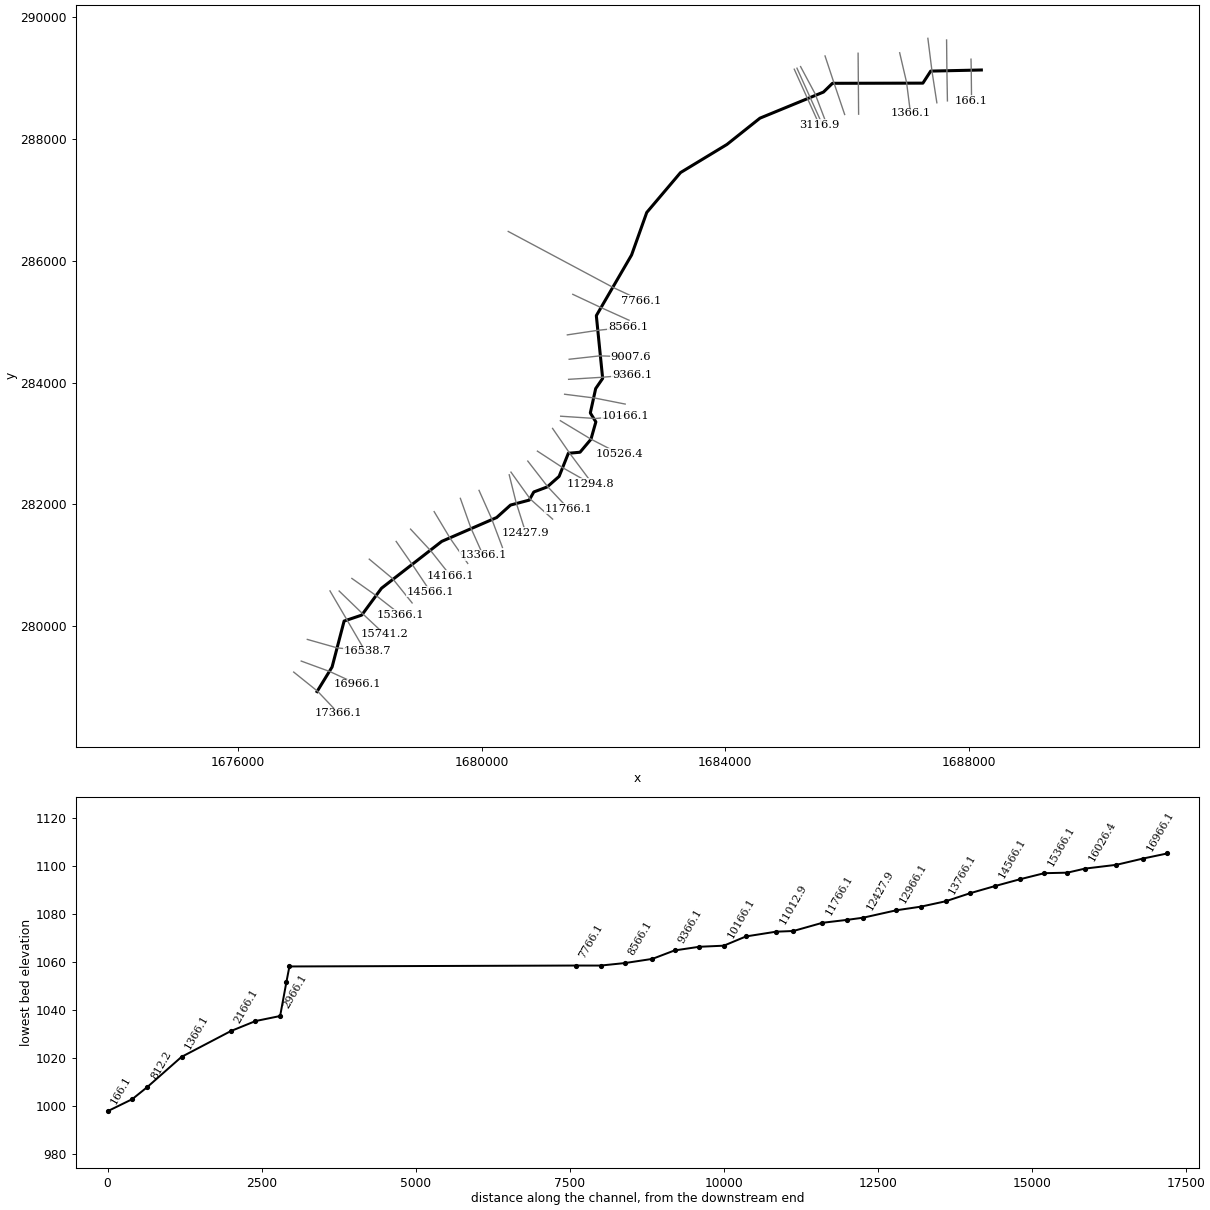
--- HallsRn.prj (project) ---

Proj Title=HallsRn
Current Plan=p01
Geom File=g01
Flow File=f01
Plan File=p01
DSS Export Rating Curves=0
DSS Export Rating Curve Sorted=0
DSS Export Volume Flow Curves=0
DXF OffsetX=0
DXF OffsetY=0
DXF ScaleX=0
DXF ScaleY=0

--- HallsRn.p01 (plan) ---

Plan Title=Floodplain
Program Version=4.00
Geom File=g01
Flow File=f01
K Sum by GR=0
Std Step Tol=0.01
Critical Tol=0.01
Num of Std Step Trials=20
Max Error Tol=0.3
Flow Tol Ratio=0.001
Split Flow NTrial=30
Split Flow Tol=0.02
Split Flow Ratio=0.02
Log Output Level=0
Friction Slope Method=1
Unsteady Friction Slope Method=2
Unsteady Bridges Friction Slope Method=1
Global Log Level=0
CheckData=False
Run HTab=0
Run UNet=0
Run PostProcess=0
UNET Theta=0
UNET Theta Warmup=0
UNET ZTol=0
UNET ZSATol=0
UNET MxIter=0
UNET MaxInSteps=0
UNET DtIC=0
UNET DtMin=0
UNET MaxCRTS=0
UNET WFStab=0
UNET SFStab=0
UNET WFX=0
UNET SFX=0
UNET DSS MLevel=0
UNET DZMax Abort=0
UNET Convert EG Bridges=0
UNET Use Existing IB Tables=0
UNET Froude Limit=0
UNET Froude Power=0
Write IC File=0
Echo Input=False
Echo Output=False
Write Detailed=0

--- HallsRn.f01 (steady flow) ---

Flow Title=NFF Regression Equation
Program Version=4.00
Number of Profiles=1
Profile Names=P100yr
River Rch & RM=HallsRn,Main      ,17366.1
     722
River Rch & RM=HallsRn,Main      ,15366.1
796.5905
River Rch & RM=HallsRn,Main      ,13766.1
881.7333
River Rch & RM=HallsRn,Main      ,10526.4
968.6223
River Rch & RM=HallsRn,Main      ,8566.1
1060.403
River Rch & RM=HallsRn,Main      ,3068.3
1250.170
River Rch & RM=HallsRn,Main      ,166.1
1370.047
Boundary for River Rch & Prof#=HallsRn,Main      ,1
Up Type=0
Dn Type=3
Dn Slope=0.007

--- HallsRn.g01 (geometry) ---

Geom Title=USGS 3m DEM
Program Version=4.00

River Reach=HallsRn     ,Main
Reach XY= 30
     1677295.657      278926.440     1677542.855      279330.602
     1677740.217      280085.005     1678029.655      280182.444
     1678354.137      280623.565     1679343.896      281393.486
     1680246.775      281785.646     1680474.295      281990.367
     1680781.497      282071.726     1680856.615      282205.406
     1681076.695      282288.206     1681272.297      282461.006
     1681424.215      282840.927     1681615.976      282858.205
     1681795.497      283071.325     1681876.135      283356.687
     1681784.936      283503.567     1681873.016      283903.884
     1681987.735      284070.445     1681883.815      285101.966
     1682462.889      286098.377     1682712.057      286797.076
     1683266.907      287452.106     1684029.824      287914.481
     1684571.830      288346.031     1685615.164      288774.734
     1685763.100      288918.696     1687248.465      288921.430
     1687376.902      289119.223     1688209.080      289137.421

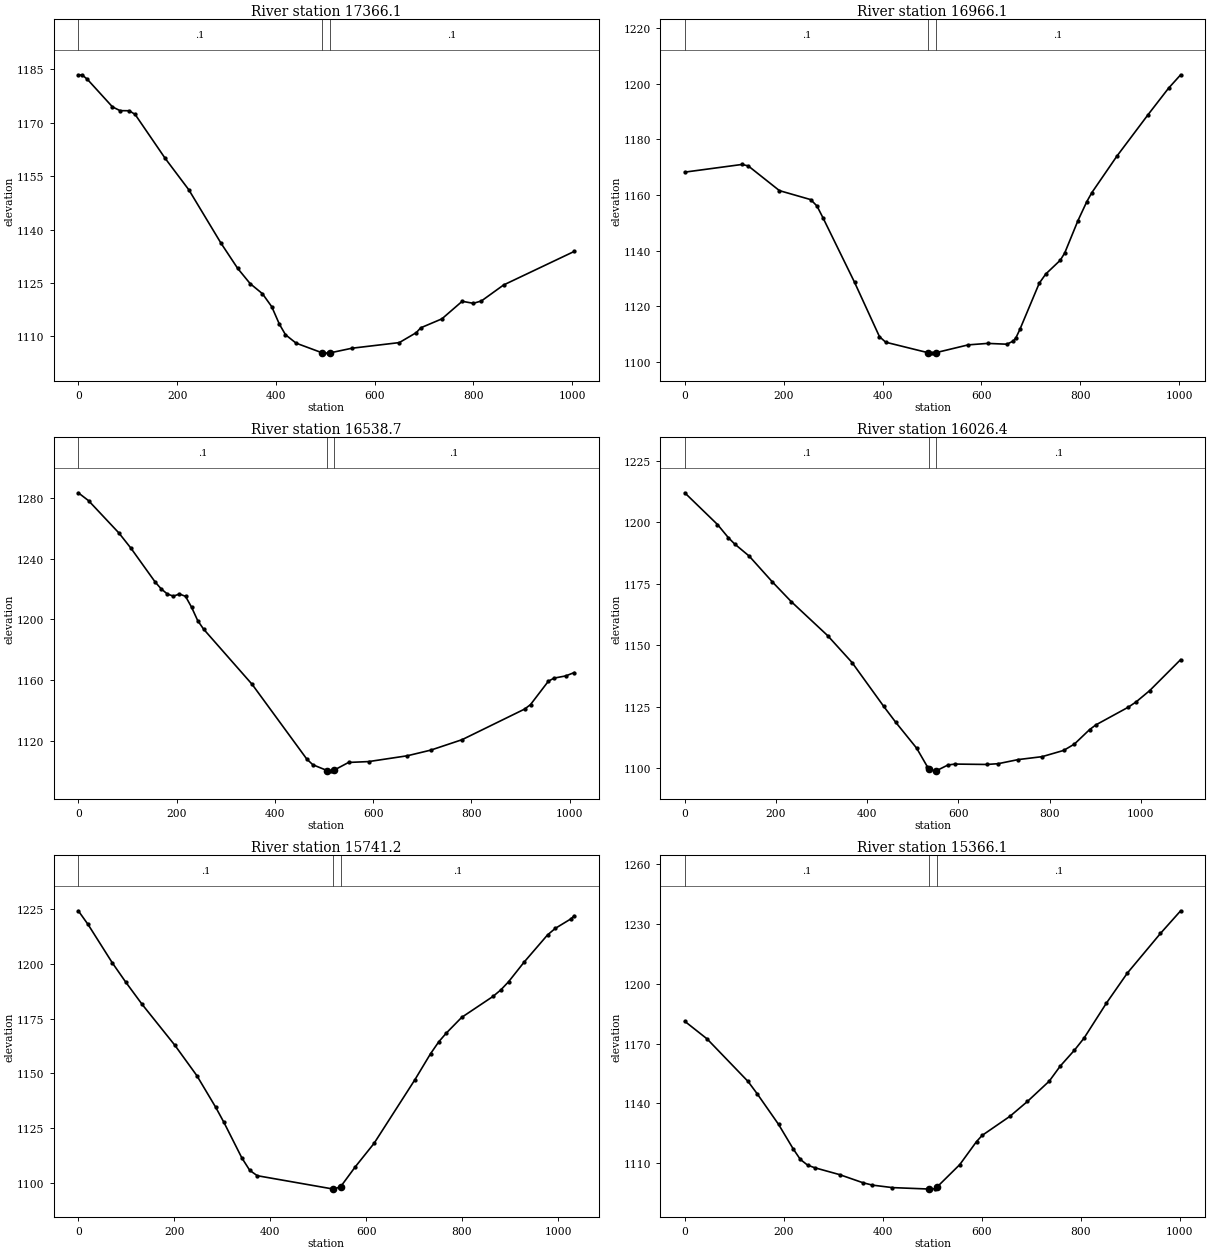
Type RM Length L Ch R = 1 ,17366.1,392.311,400,407.742
XS GIS Cut Line= 3
     1676912.016      279246.767     1677303.021      278932.988
     1677649.644      278568.288
#Sta/Elev= 30
       0 1183.49     8.3 1183.40    18.5 1182.20    69.1 1174.48    84.5 1173.42
   103.0 1173.39   114.9 1172.37   175.8 1160.01   223.8 1151.15   288.8 1136.17
   322.6 1129.08   347.9 1124.79   372.7 1121.97   391.6 1118.30   407.0 1113.41
   419.4 1110.43   440.8 1108.07   493.8 1105.34   504.9 1105.26   508.8 1105.31
   554.0 1106.64   649.8 1108.22   684.3 1111.03   693.1 1112.37   736.0 1114.89
   777.1 1119.83   799.7 1119.26   816.1 1119.93   861.0 1124.42  1003.8 1133.84
#Mann= 3 , 0 , 0
       0     0.1       0   493.8   0.045       0   508.8     0.1       0
Bank Sta=   493.8,   508.8
Exp/Cntr=0.3,0.1

Type RM Length L Ch R = 1 ,16966.1,424.511,427.483,434.625
XS GIS Cut Line= 3
     1677035.635      279427.494     1677505.187      279255.316
     1677961.918      279045.482
#Sta/Elev= 30
       0 1168.24   115.5 1171.00   128.2 1170.49   191.4 1161.58   254.6 1158.35
   267.3 1156.05   279.9 1151.64   343.2 1128.62   393.7 1109.02   406.4 1107.02
   492.6 1103.22   499.7 1103.10   507.6 1103.26   573.1 1106.07   612.3 1106.60
   651.5 1106.31   664.6 1107.49   669.8 1108.69   677.6 1111.62   716.8 1128.26
   729.9 1131.56   759.3 1136.53   768.3 1139.14   795.1 1150.80   813.0 1157.63
   823.3 1160.90   873.6 1173.94   937.1 1188.98   978.2 1198.43  1002.7 1203.26
#Mann= 3 , 0 , 0
       0     0.1       0   492.6   0.045       0   507.6     0.1       0
Bank Sta=   492.6,   507.6
Exp/Cntr=0.3,0.1

Type RM Length L Ch R = 1 ,16538.7,530.486,512.292,491.375
XS GIS Cut Line= 3
     1677135.992      279783.171     1677624.424      279645.004
     1678122.759      279590.000
#Sta/Elev= 30
       0 1283.09    20.8 1277.95    82.5 1256.77   107.1 1246.74   156.5 1224.51
   168.8 1220.02   181.2 1216.70   193.5 1215.31   205.8 1216.71   218.2 1215.17
   230.5 1208.00   242.9 1199.27   254.9 1193.67   353.9 1157.35   465.0 1108.38
   477.3 1104.68   506.2 1100.90   514.1 1100.51   521.2 1101.28   549.9 1106.21
   590.8 1106.77   669.4 1110.58   717.2 1114.29   780.9 1121.14   908.3 1141.24
   920.2 1144.17   956.5 1159.48   968.0 1161.53   991.9 1162.97  1009.0 1165.16
#Mann= 3 , 0 , 0
       0     0.1       0   506.2   0.045       0   521.2     0.1       0
Bank Sta=   506.2,   521.2
Exp/Cntr=0.3,0.1

Type RM Length L Ch R = 1 ,16026.4,279.293,285.184,291.412
XS GIS Cut Line= 3
     1677508.314      280580.064     1677755.338      280158.368
     1678057.010      279641.373
#Sta/Elev= 30
       0 1212.06    71.7 1199.18    95.6 1193.81   109.3 1191.27   141.2 1186.34
   191.9 1175.87   233.2 1167.87   313.0 1154.05   366.8 1143.06   436.2 1125.24
   462.2 1118.85   508.3 1108.27   531.6 1100.80   536.1 1099.72   549.6 1098.92
   551.1 1099.03   577.1 1101.42   592.4 1101.79   661.9 1101.63   687.0 1101.94
   731.3 1103.62   783.4 1104.80   830.7 1107.34   854.3 1109.92   887.5 1115.79
   901.4 1117.72   972.1 1124.88   989.4 1127.03  1019.2 1131.63  1087.2 1144.25
#Mann= 3 , 0 , 0
       0     0.1       0   536.1   0.045       0   551.1     0.1       0
Bank Sta=   536.1,   551.1
Exp/Cntr=0.3,0.1

Type RM Length L Ch R = 1 ,15741.2,371.579,375.041,377.121
XS GIS Cut Line= 3
     1677658.793      280577.975     1678045.867      280203.937
     1678407.456      279865.272
#Sta/Elev= 30
       0 1224.08    20.3 1217.85    70.7 1200.42    98.6 1191.66   132.7 1181.53
   201.1 1162.85   247.0 1148.99   286.5 1134.50   303.6 1127.62   340.9 1111.46
   357.4 1105.79   373.0 1103.35   531.8 1097.25   532.5 1097.23   546.8 1098.32
   577.6 1107.46   616.5 1118.08   701.7 1147.11   734.2 1158.92   751.3 1164.34
   766.8 1168.28   799.3 1175.53   864.4 1185.05   880.6 1188.00   896.9 1191.74
   929.4 1200.71   978.2 1213.10   994.4 1216.09  1027.0 1220.42  1033.7 1221.80
#Mann= 3 , 0 , 0
       0     0.1       0   531.8   0.045       0   546.8     0.1       0
Bank Sta=   531.8,   546.8
Exp/Cntr=0.3,0.1

Type RM Length L Ch R = 1 ,15366.1,402.056,400,394.393
XS GIS Cut Line= 3
     1677867.815      280785.140     1678276.754      280495.443
     1678671.218      280187.574
#Sta/Elev= 30
       0 1181.16    44.8 1172.39   127.7 1151.02   146.1 1144.87   189.3 1129.51
   218.9 1117.21   233.4 1111.90   248.0 1109.05   262.5 1107.73   312.6 1104.29
   359.9 1100.21   378.9 1099.02   419.5 1097.77   493.7 1097.05   495.3 1097.01
   504.7 1097.23   508.7 1097.87   555.4 1109.31   589.3 1120.87   600.6 1123.95
   656.9 1133.56   692.1 1140.98   736.1 1151.15   758.4 1158.73   787.1 1166.71
   806.4 1172.73   851.5 1190.25   893.8 1205.32   960.8 1225.25  1001.5 1236.57
#Mann= 3 , 0 , 0
       0     0.1       0   493.7   0.045       0   508.7     0.1       0
Bank Sta=   493.7,   508.7
Exp/Cntr=0.3,0.1

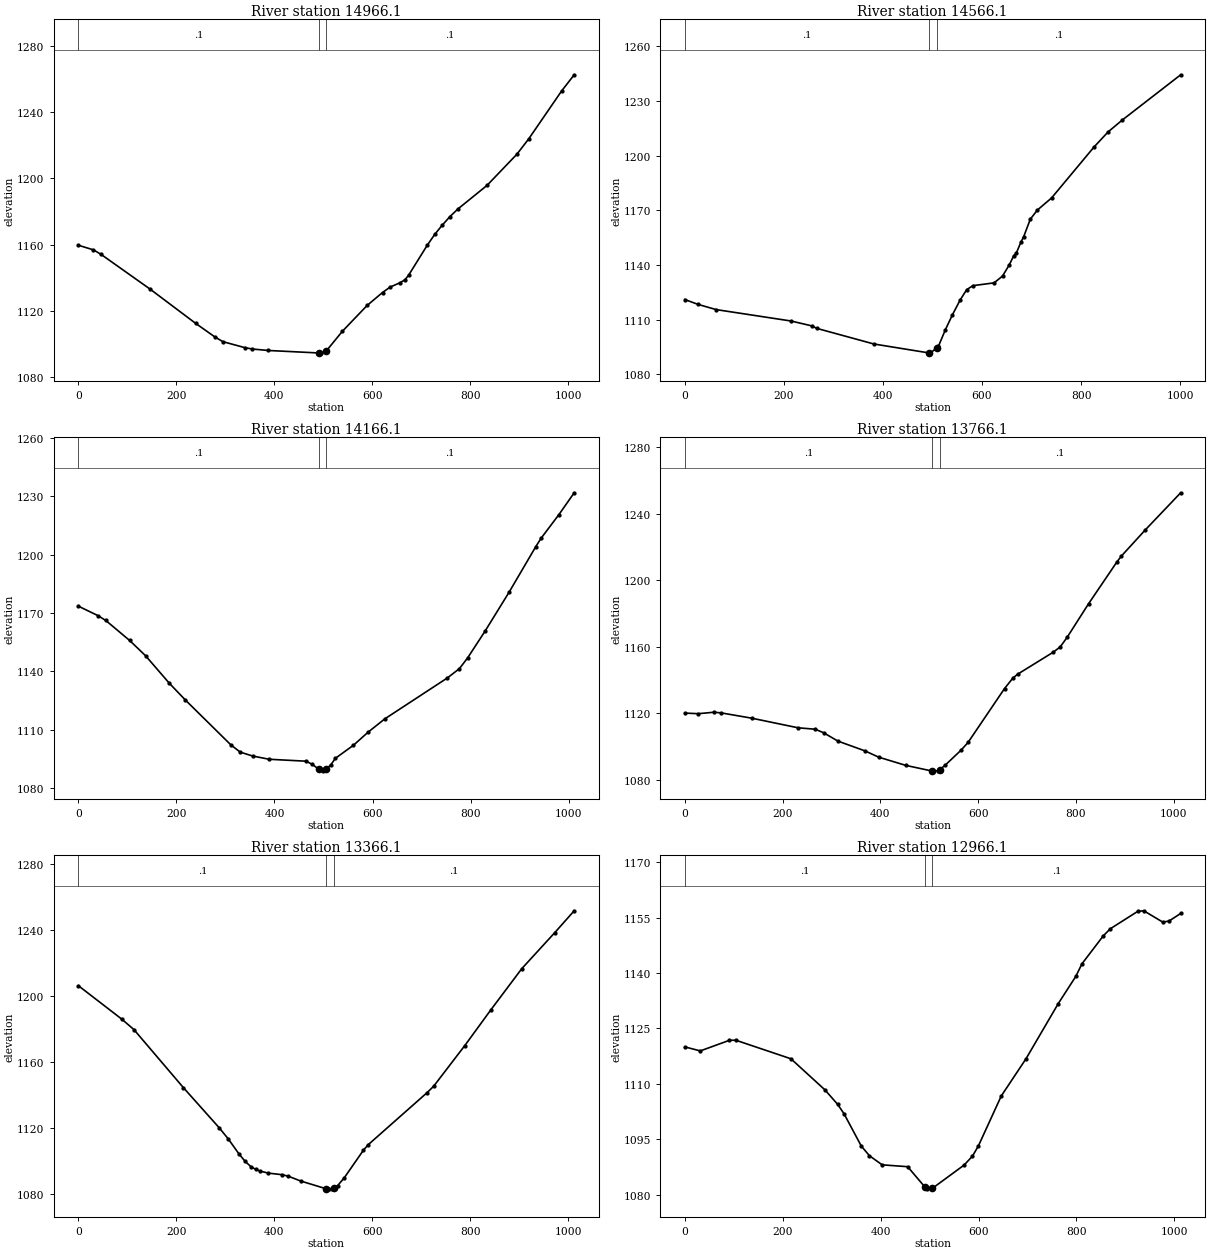
Type RM Length L Ch R = 1 ,14966.1,406.158,400,398.012
XS GIS Cut Line= 3
     1678153.299      281101.791     1678536.221      280783.002
     1678857.555      280382.683
#Sta/Elev= 30
       0 1159.56    30.9 1156.76    46.3 1154.05   146.4 1133.07   239.2 1112.44
   278.0 1104.33   294.8 1101.37   339.8 1097.75   355.3 1096.91   387.6 1096.04
   490.8 1094.53   494.3 1094.44   505.8 1095.72   538.7 1107.62   589.3 1123.24
   620.6 1131.02   635.8 1134.23   656.9 1137.03   666.3 1138.69   673.8 1141.44
   712.0 1159.61   727.2 1166.12   742.4 1171.66   758.2 1176.86   775.1 1181.61
   833.8 1195.67   894.7 1214.47   918.7 1223.67   986.0 1252.66  1011.6 1262.41
#Mann= 3 , 0 , 0
       0     0.1       0   490.8   0.045       0   505.8     0.1       0
Bank Sta=   490.8,   505.8
Exp/Cntr=0.3,0.1

Type RM Length L Ch R = 1 ,14566.1,394.409,400,402.435
XS GIS Cut Line= 3
     1678595.505      281392.616     1678881.573      280981.795
     1679159.762      280565.752
#Sta/Elev= 30
       0 1121.07    26.7 1118.39    63.4 1115.53   214.4 1109.27   257.0 1106.55
   266.0 1105.26   381.7 1096.65   493.1 1091.74   495.8 1091.64   508.1 1094.50
   511.8 1095.29   526.1 1104.55   540.3 1112.73   555.7 1120.75   568.9 1126.46
   581.4 1128.67   624.2 1130.20   641.3 1133.93   654.6 1139.93   664.2 1145.21
   668.9 1146.42   678.3 1152.46   684.1 1155.59   697.4 1165.17   711.7 1170.17
   740.3 1176.81   826.0 1204.77   854.5 1213.09   883.1 1219.59  1000.8 1244.39
#Mann= 3 , 0 , 0
       0     0.1       0   493.1   0.045       0   508.1     0.1       0
Bank Sta=   493.1,   508.1
Exp/Cntr=0.3,0.1

Type RM Length L Ch R = 1 ,14166.1,405.336,400,398.801
XS GIS Cut Line= 3
     1678831.678      281595.253     1679171.019      281230.432
     1679489.086      280828.031
#Sta/Elev= 30
       0 1173.51    39.7 1168.67    56.0 1166.14   104.6 1155.86   137.0 1148.04
   185.7 1133.83   218.1 1125.30   311.3 1102.13   330.2 1098.46   355.4 1096.47
   389.1 1094.79   464.7 1093.79   477.5 1092.10   490.7 1089.60   498.2 1088.69
   505.7 1089.65   515.2 1092.02   524.3 1095.29   561.0 1101.98   591.2 1108.77
   625.0 1115.55   752.5 1136.58   777.2 1141.37   794.1 1146.97   829.1 1160.50
   878.6 1180.72   932.9 1204.07   943.9 1208.47   980.1 1220.56  1011.2 1231.76
#Mann= 3 , 0 , 0
       0     0.1       0   490.7   0.045       0   505.7     0.1       0
Bank Sta=   490.7,   505.7
Exp/Cntr=0.3,0.1

Type RM Length L Ch R = 1 ,13766.1,403.919,400,395.701
XS GIS Cut Line= 3
     1679219.594      281882.105     1679483.794      281441.726
     1679770.881      281032.066
#Sta/Elev= 30
       0 1120.21    27.4 1119.84    58.8 1120.69    73.6 1120.36   136.7 1117.15
   231.9 1111.34   266.5 1110.51   283.8 1108.37   313.1 1103.35   368.5 1097.46
   396.3 1093.72   451.5 1088.78   506.1 1085.32   506.9 1085.30   517.4 1085.56
   521.1 1086.15   532.9 1089.01   564.6 1097.82   579.1 1102.52   653.8 1134.98
   670.9 1141.27   680.6 1143.60   753.1 1156.77   767.6 1159.99   782.1 1165.91
   825.5 1185.92   883.5 1211.09   892.5 1214.57   941.5 1230.33  1013.8 1252.65
#Mann= 3 , 0 , 0
       0     0.1       0   506.1   0.045       0   521.1     0.1       0
Bank Sta=   506.1,   521.1
Exp/Cntr=0.3,0.1

Type RM Length L Ch R = 1 ,13366.1,396.563,400,397.872
XS GIS Cut Line= 3
     1679650.031      282100.538     1679822.039      281616.466
     1680025.280      281161.877
#Sta/Elev= 30
       0 1206.48    88.3 1186.25   113.5 1179.81   214.3 1144.64   287.7 1120.19
   306.3 1113.38   327.7 1104.45   340.3 1099.92   352.2 1096.69   362.0 1095.02
   371.3 1093.98   387.7 1092.78   415.9 1091.82   428.5 1090.90   453.7 1087.99
   506.2 1083.23   510.8 1083.07   516.8 1083.21   521.2 1083.89   528.9 1085.12
   542.8 1090.02   581.8 1106.71   591.8 1110.10   711.9 1141.66   724.9 1145.43
   788.5 1170.11   841.9 1191.88   904.8 1216.78   972.0 1238.58  1011.7 1251.86
#Mann= 3 , 0 , 0
       0     0.1       0   506.2   0.045       0   521.2     0.1       0
Bank Sta=   506.2,   521.2
Exp/Cntr=0.3,0.1

Type RM Length L Ch R = 1 ,12966.1,542.286,538.275,535.79
XS GIS Cut Line= 3
     1679956.878      282231.245     1680159.495      281776.462
     1680340.972      281294.450
#Sta/Elev= 30
       0 1120.02    31.7 1118.94    91.2 1121.81   104.2 1121.83   216.8 1116.81
   286.2 1108.41   312.2 1104.49   325.2 1101.96   360.6 1093.19   377.2 1090.58
   403.2 1088.12   455.2 1087.62   490.4 1082.14   495.5 1081.55   505.4 1081.73
   570.4 1088.04   587.6 1090.46   599.7 1093.22   646.5 1106.75   697.2 1116.85
   762.7 1131.69   798.7 1139.08   811.4 1142.51   854.9 1150.06   869.3 1151.98
   925.6 1156.71   937.8 1156.83   976.3 1153.79   989.0 1154.05  1012.9 1156.11
#Mann= 3 , 0 , 0
       0     0.1       0   490.4   0.045       0   505.4     0.1       0
Bank Sta=   490.4,   505.4
Exp/Cntr=0.3,0.1

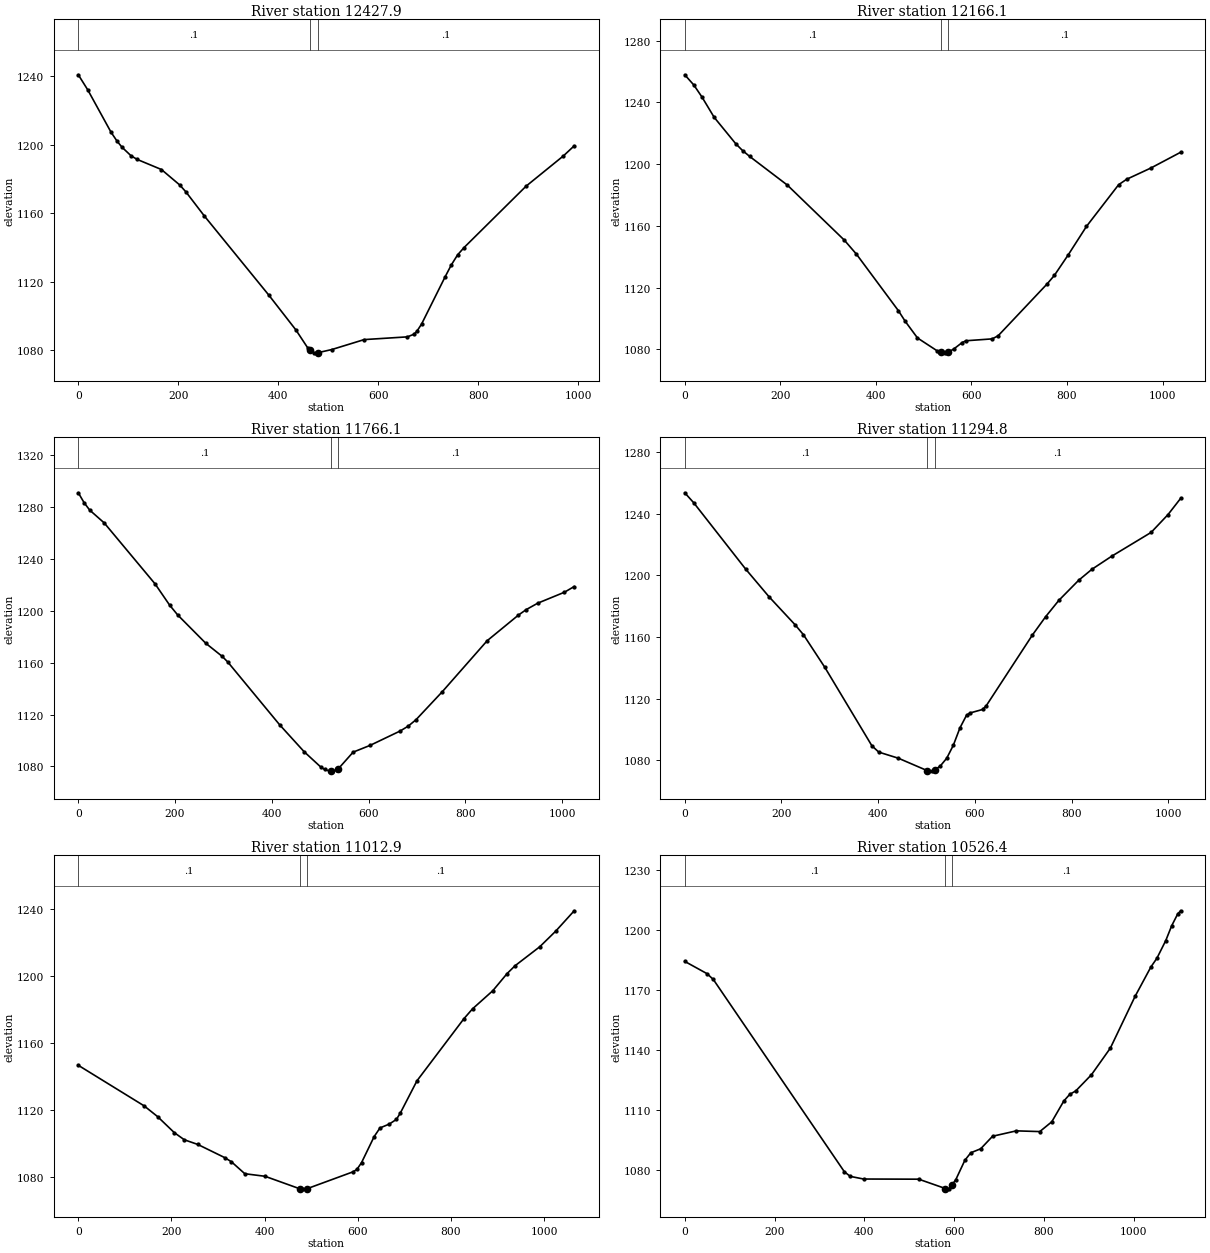
Type RM Length L Ch R = 1 ,12427.9,254.21,261.725,273.279
XS GIS Cut Line= 3
     1680452.636      282487.312     1680564.690      282037.070
     1680724.727      281533.836
#Sta/Elev= 30
       0 1240.69    18.8 1231.95    65.5 1207.20    77.6 1201.98    87.4 1198.48
   105.1 1193.60   117.3 1191.43   166.2 1185.50   202.9 1176.47   215.2 1172.47
   251.9 1158.49   381.3 1112.20   435.4 1091.93   459.6 1081.23   463.7 1080.25
   472.3 1078.46   478.7 1078.67   507.1 1080.55   571.9 1086.35   658.3 1087.94
   671.6 1089.49   677.2 1091.14   686.7 1095.39   733.9 1122.98   746.3 1129.91
   758.8 1135.74   771.7 1139.99   895.8 1175.78   970.6 1193.46   992.0 1199.27
#Mann= 3 , 0 , 0
       0     0.1       0   463.7   0.045       0   478.7     0.1       0
Bank Sta=   463.7,   478.7
Exp/Cntr=0.3,0.1

Type RM Length L Ch R = 1 ,12166.1,397.635,400,398.451
XS GIS Cut Line= 3
     1680481.152      282531.406     1680798.124      282089.277
     1681165.595      281759.649
#Sta/Elev= 30
       0 1257.93    18.9 1251.33    36.0 1243.51    61.5 1230.37   106.7 1213.24
   120.8 1208.88   135.9 1205.01   214.7 1186.44   333.8 1150.80   359.3 1141.67
   446.9 1105.11   461.4 1098.13   487.0 1087.37   528.4 1078.99   536.5 1078.25
   545.1 1077.55   551.5 1078.27   562.9 1080.22   580.1 1084.32   588.5 1085.57
   643.4 1086.79   655.8 1088.80   758.5 1122.47   773.5 1127.94   802.9 1141.45
   840.7 1159.71   908.0 1186.73   924.8 1190.24   975.3 1197.50  1037.7 1207.73
#Mann= 3 , 0 , 0
       0     0.1       0   536.5   0.045       0   551.5     0.1       0
Bank Sta=   536.5,   551.5
Exp/Cntr=0.3,0.1

Type RM Length L Ch R = 1 ,11766.1,462.193,471.394,477.203
XS GIS Cut Line= 3
     1680757.948      282712.624     1681082.900      282294.045
     1681422.363      281933.355
#Sta/Elev= 30
       0 1290.96    11.9 1283.37    23.5 1277.64    53.6 1267.72   158.8 1220.67
   188.8 1204.33   205.5 1196.74   263.6 1174.91   297.7 1164.76   309.1 1160.44
   416.1 1112.12   466.9 1091.30   500.8 1079.66   509.2 1077.60   519.5 1076.33
   522.4 1076.47   534.2 1077.04   537.4 1078.07   568.2 1090.97   603.5 1096.23
   665.4 1107.27   681.7 1110.93   698.0 1115.89   752.9 1137.72   845.3 1176.89
   909.9 1196.65   926.2 1200.93   949.9 1205.85  1004.9 1214.27  1025.2 1218.67
#Mann= 3 , 0 , 0
       0     0.1       0   522.4   0.045       0   537.4     0.1       0
Bank Sta=   522.4,   537.4
Exp/Cntr=0.3,0.1

Type RM Length L Ch R = 1 ,11294.8,290.671,281.826,272.199
XS GIS Cut Line= 3
     1680915.988      282876.069     1681345.728      282595.864
     1681791.799      282343.461
#Sta/Elev= 30
       0 1253.64    18.5 1247.17   125.6 1204.23   174.4 1186.08   228.5 1167.83
   245.3 1161.54   289.8 1140.23   387.0 1089.37   401.2 1085.26   441.9 1081.28
     502 1073.16   511.6 1072.91     517 1073.72   528.2 1076.14   541.8 1081.29
   555.4 1089.67   569.1 1100.96   582.7 1109.16   590.0 1110.68   616.2 1112.97
   623.6 1115.40   719.1 1161.34   746.4 1173.20   773.7 1183.80   814.6 1196.82
   841.9 1203.94   882.8 1212.43   964.6 1227.94   999.5 1239.50  1025.6 1250.03
#Mann= 3 , 0 , 0
       0     0.1       0     502   0.045       0     517     0.1       0
Bank Sta=     502,     517
Exp/Cntr=0.3,0.1

Type RM Length L Ch R = 1 ,11012.9,476.846,486.481,497.187
XS GIS Cut Line= 3
     1681164.840      283249.545     1681445.754      282841.953
     1681786.196      282385.538
#Sta/Elev= 30
       0 1146.70   141.1 1122.47   170.0 1116.05   206.1 1106.40   227.6 1102.14
   256.5 1099.35   314.2 1091.48   328.6 1089.00   357.4 1081.83   400.7 1080.31
   476.2 1072.75   479.2 1072.62   491.2 1072.89   589.5 1082.95   598.0 1084.41
   607.9 1088.44   635.1 1104.07   647.6 1109.25   667.5 1111.54   682.9 1114.37
   691.3 1118.18   727.0 1137.46   827.6 1174.55   846.2 1180.49   889.8 1191.36
   920.4 1201.59   937.4 1206.26   990.6 1217.66  1024.9 1227.01  1064.4 1239.15
#Mann= 3 , 0 , 0
       0     0.1       0   476.2   0.045       0   491.2     0.1       0
Bank Sta=   476.2,   491.2
Exp/Cntr=0.3,0.1

Type RM Length L Ch R = 1 ,10526.4,350.743,360.299,373.345
XS GIS Cut Line= 3
     1681292.641      283376.155     1681796.136      283072.699
     1682255.065      282836.034
#Sta/Elev= 30
       0 1184.25    49.6 1178.13    63.5 1175.25   355.4 1079.30   368.5 1077.01
   398.1 1075.69   521.0 1075.61   580.4 1070.95   587.9 1070.65   595.4 1072.90
   603.5 1075.37   623.7 1085.04   636.9 1088.78   659.0 1090.79   685.4 1097.03
   738.3 1099.72   790.6 1099.36   817.3 1104.25   844.0 1114.59   857.3 1117.94
   870.7 1119.65   905.7 1127.74   947.7 1141.00  1002.7 1166.79  1037.9 1181.44
  1051.4 1185.84  1071.1 1194.65  1084.4 1202.08  1097.8 1207.99  1104.2 1209.49
#Mann= 3 , 0 , 0
       0     0.1       0   580.4   0.045       0   595.4     0.1       0
Bank Sta=   580.4,   595.4
Exp/Cntr=0.3,0.1

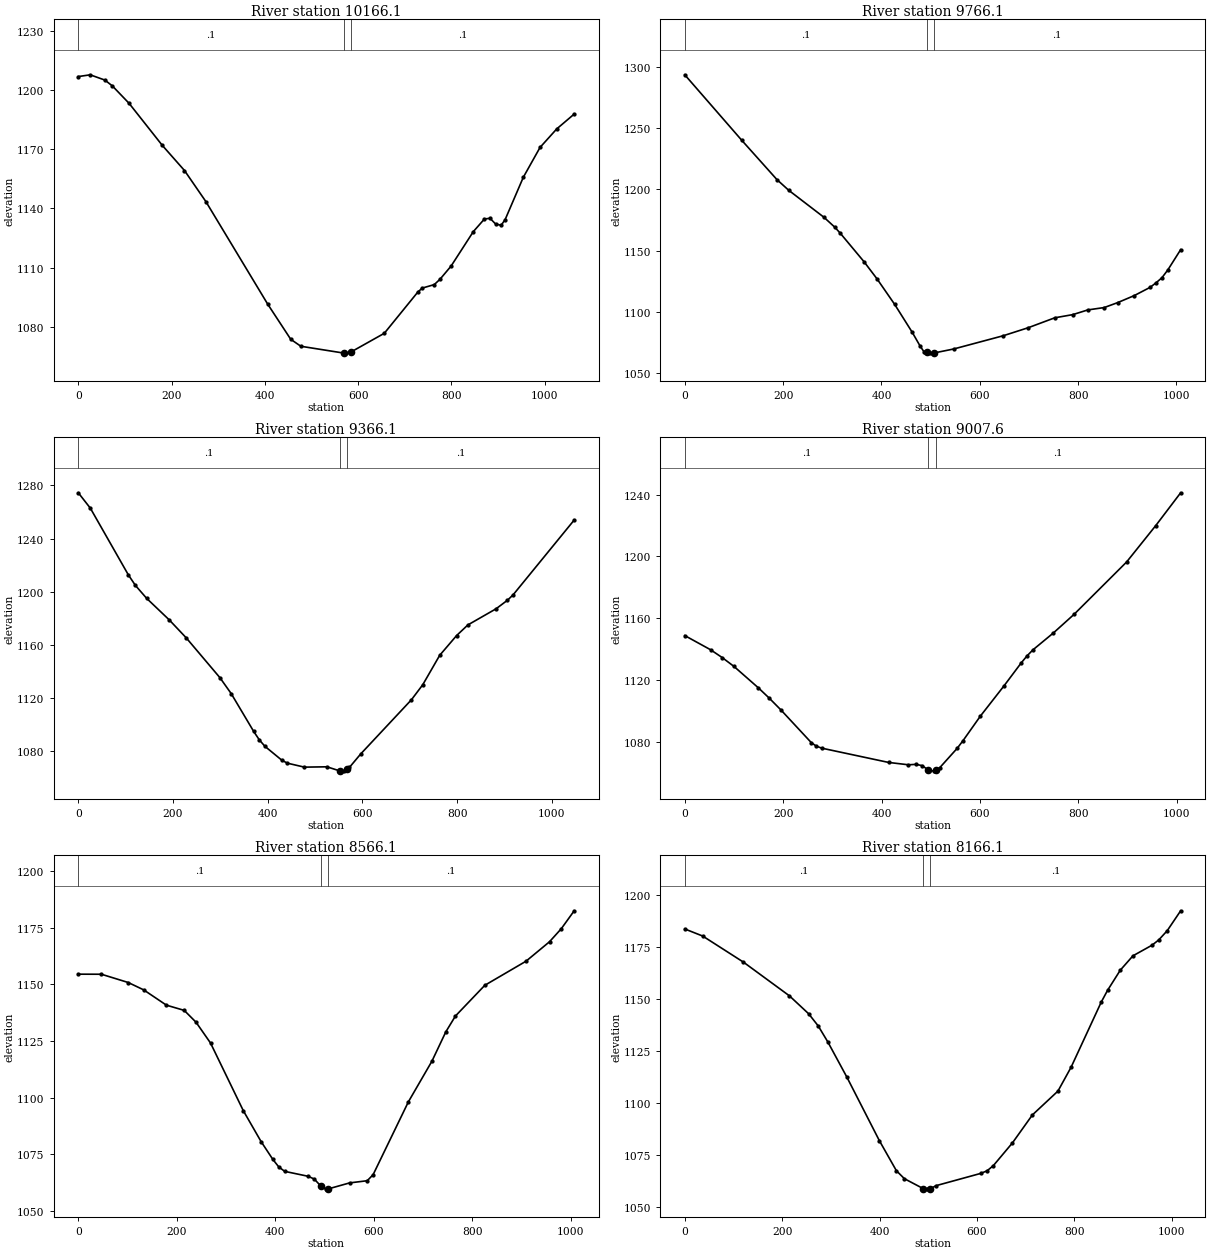
Type RM Length L Ch R = 1 ,10166.1,399.83,400,393.594
XS GIS Cut Line= 3
     1681297.867      283449.948     1681873.206      283412.108
     1682357.756      283459.832
#Sta/Elev= 30
       0 1206.74    25.5 1207.61    57.0 1204.95    73.1 1201.97   108.8 1193.20
   180.1 1171.91   227.7 1159.19   273.5 1143.50   406.2 1091.57   455.6 1073.79
   477.3 1070.26   569.1 1066.82   572.8 1066.79   584.1 1067.27   656.3 1076.83
   727.9 1097.61   737.5 1099.69   763.4 1101.46   775.6 1104.13   799.5 1110.83
   847.2 1128.27   871.0 1134.65   883.0 1135.02   894.9 1132.15   906.8 1131.48
   915.4 1134.32   954.5 1155.80   990.3 1170.87  1026.1 1180.24  1063.5 1187.74
#Mann= 3 , 0 , 0
       0     0.1       0   569.1   0.045       0   584.1     0.1       0
Bank Sta=   569.1,   584.1
Exp/Cntr=0.3,0.1

Type RM Length L Ch R = 1 ,9766.1,396.041,400,405.242
XS GIS Cut Line= 3
     1681362.906      283810.795     1681858.298      283748.131
     1682357.923      283649.284
#Sta/Elev= 30
       0 1293.45   115.6 1240.15   187.4 1207.96   211.4 1199.22   283.2 1177.15
   305.1 1169.11   315.8 1164.40   364.5 1140.97   390.9 1127.00   426.8 1106.18
   462.7 1083.29   478.7 1072.07   486.6 1067.39   491.8 1066.94   498.6 1066.33
   506.8 1066.45   547.0 1069.71   648.1 1080.56   698.6 1087.07   752.7 1095.17
   789.0 1097.73   819.8 1101.59   853.1 1103.52   880.4 1107.53   914.2 1113.27
   946.4 1119.98   958.5 1123.68   970.6 1127.87   982.7 1134.31  1008.6 1150.73
#Mann= 3 , 0 , 0
       0     0.1       0   491.8   0.045       0   506.8     0.1       0
Bank Sta=   491.8,   506.8
Exp/Cntr=0.3,0.1

Type RM Length L Ch R = 1 ,9366.1,357.26,358.506,356.59
XS GIS Cut Line= 3
     1681428.487      284055.862     1681987.056      284090.298
     1682472.981      284131.005
#Sta/Elev= 30
       0 1274.47    25.4 1262.89   105.7 1212.63   120.6 1204.69   144.4 1194.94
   192.0 1178.75   227.7 1165.29   299.0 1135.23   322.8 1123.26   370.4 1094.70
   382.3 1088.34   394.2 1083.46   429.9 1073.00   441.7 1070.78   477.5 1067.80
   525.0 1068.06   552.1 1064.99   560.7 1064.80   567.1 1066.36   572.6 1067.59
   596.5 1077.76   703.7 1118.62   727.5 1129.88   763.3 1152.06   799.0 1166.94
   822.8 1174.94   882.4 1187.11   906.2 1193.49   918.2 1197.55  1047.3 1253.94
#Mann= 3 , 0 , 0
       0     0.1       0   552.1   0.045       0   567.1     0.1       0
Bank Sta=   552.1,   567.1
Exp/Cntr=0.3,0.1

Type RM Length L Ch R = 1 ,9007.6,440.776,441.494,442.936
XS GIS Cut Line= 3
     1681437.530      284385.598     1681940.786      284441.158
     1682442.294      284425.623
#Sta/Elev= 30
       0 1148.87    52.3 1139.74    76.2 1134.64   100.1 1128.91   149.6 1115.10
   171.1 1108.64   195.6 1100.78   257.1 1079.74   267.3 1077.44   278.6 1076.12
   414.2 1066.92   454.5 1065.39   470.3 1065.66   482.3 1064.87   494.8 1062.12
   506.2 1061.29   509.8 1061.90   518.1 1063.42   553.7 1075.99   565.6 1080.95
   601.2 1096.94   648.7 1116.26   684.4 1131.39   696.2 1135.90   708.1 1139.73
   749.5 1150.60   791.3 1162.55   898.2 1196.40   957.6 1219.98  1008.1 1241.12
#Mann= 3 , 0 , 0
       0     0.1       0   494.8   0.045       0   509.8     0.1       0
Bank Sta=   494.8,   509.8
Exp/Cntr=0.3,0.1

Type RM Length L Ch R = 1 ,8566.1,413.387,400,387.913
XS GIS Cut Line= 3
     1681407.509      284786.057     1681902.264      284860.171
     1682405.923      284913.776
#Sta/Elev= 30
       0 1154.50    46.9 1154.47   101.3 1150.82   132.6 1147.58   178.9 1140.81
   215.0 1138.51   239.0 1133.28   268.4 1124.10   335.0 1094.20   371.0 1080.59
   395.0 1072.68   407.0 1069.37   419.0 1067.41   466.7 1065.23   479.1 1064.00
   492.8 1060.83   503.1 1059.56   507.8 1059.68   550.8 1062.31   586.6 1063.27
   598.6 1065.95   670.2 1098.12   718.0 1116.07   746.2 1129.02   765.7 1136.01
   825.4 1149.59   909.0 1160.22   956.8 1168.83   980.7 1174.59  1006.8 1182.48
#Mann= 3 , 0 , 0
       0     0.1       0   492.8   0.045       0   507.8     0.1       0
Bank Sta=   492.8,   507.8
Exp/Cntr=0.3,0.1

Type RM Length L Ch R = 1 ,8166.1,400.914,400,399.975
XS GIS Cut Line= 3
     1681496.907      285452.224     1681946.692      285240.909
     1682421.627      285026.406
#Sta/Elev= 30
       0 1183.80    36.7 1180.40   120.4 1167.83   214.8 1151.60   254.2 1142.99
   273.9 1137.12   293.5 1129.47   332.9 1112.40   399.6 1081.81   434.5 1067.36
   450.9 1063.53   489.5 1058.76   497.0 1058.50   504.5 1058.79   516.4 1060.20
   607.6 1066.07   620.6 1067.31   633.6 1069.83   672.7 1080.75   713.7 1094.23
   766.2 1105.72   793.2 1117.22   855.1 1148.58   868.1 1154.26   894.2 1163.95
   920.2 1170.87   959.3 1175.98   973.3 1178.55   990.6 1182.98  1018.1 1192.54
#Mann= 3 , 0 , 0
       0     0.1       0   489.5   0.045       0   504.5     0.1       0
Bank Sta=   489.5,   504.5
Exp/Cntr=0.3,0.1

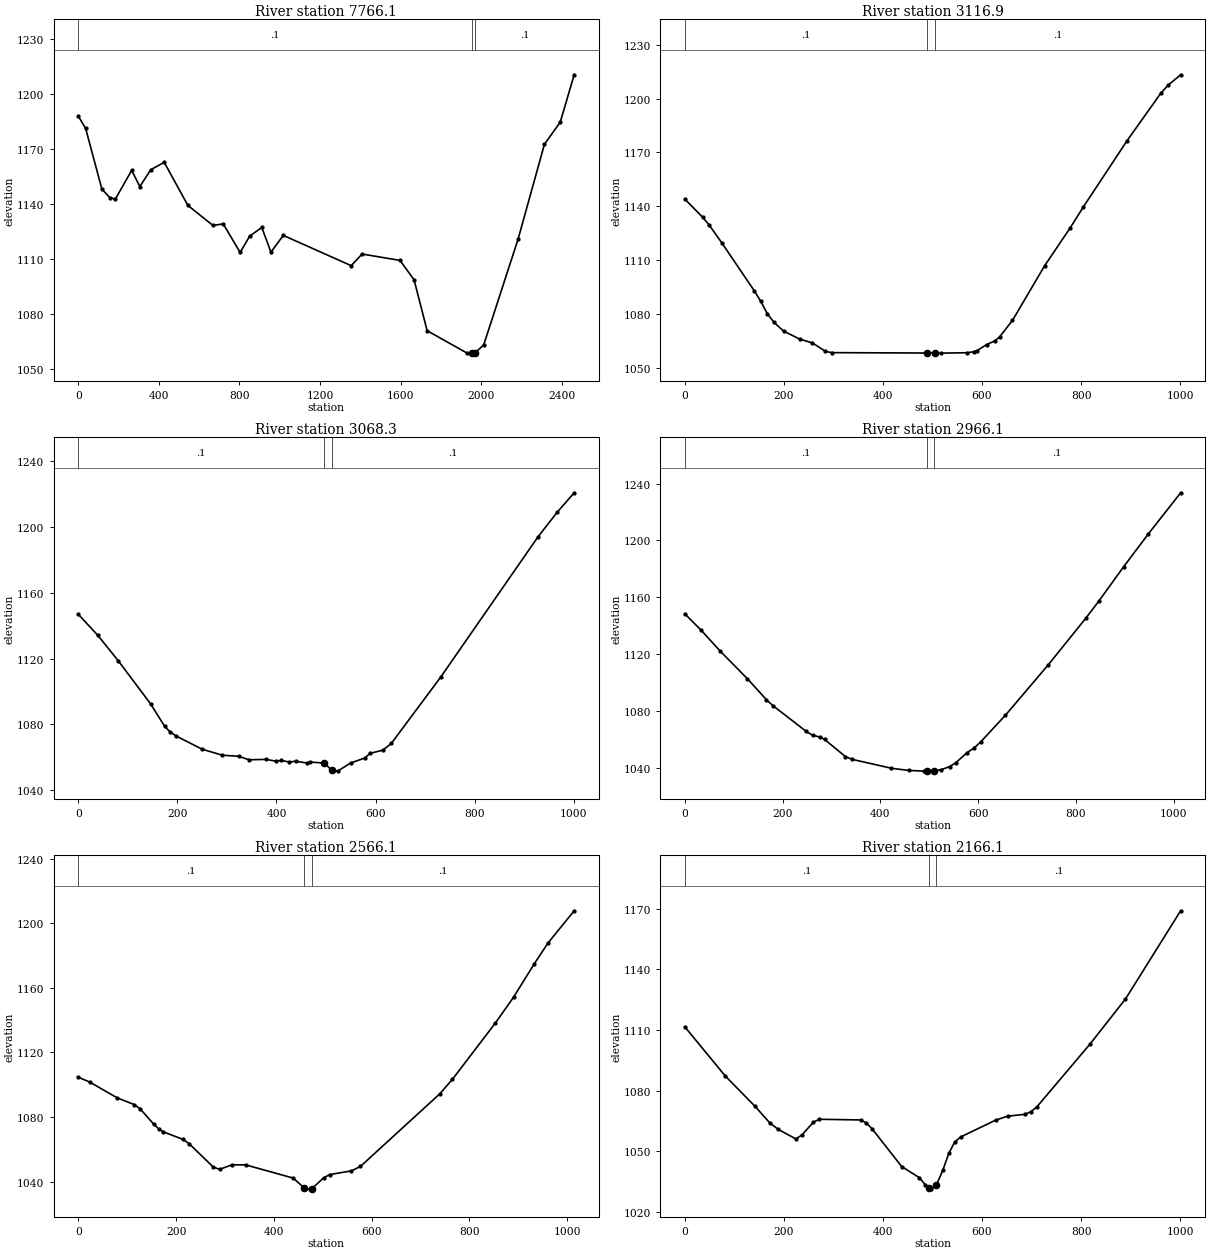
Type RM Length L Ch R = 1 ,7766.1,4664.102,4649.248,4633.169
XS GIS Cut Line= 3
     1680436.461      286485.076     1682167.142      285561.231
     1682620.684      285349.992
#Sta/Elev= 30
       0 1187.76    36.3 1181.12   117.0 1147.99   157.4 1143.24   184.2 1142.65
   265.0 1158.22   305.4 1149.38   359.3 1158.55   426.5 1162.61   544.0 1139.11
   668.8 1128.16   719.5 1129.05   803.4 1113.43   851.1 1122.38   911.0 1127.06
   956.4 1113.62  1017.8 1122.74  1355.2 1106.22  1409.0 1112.59  1597.4 1109.09
  1667.2 1098.52  1732.0 1070.76  1930.4 1058.51  1954.3 1058.51  1969.3 1058.51
  2013.2 1063.10  2183.5 1120.65  2314.4 1172.41  2393.0 1184.56  2462.1 1210.36
#Mann= 3 , 0 , 0
       0     0.1       0  1954.3   0.045       0  1969.3     0.1       0
Bank Sta=  1954.3,  1969.3
Exp/Cntr=0.3,0.1

Type RM Length L Ch R = 1 ,3116.9,48.321,48.584,48.848
XS GIS Cut Line= 3
     1685135.525      289150.243     1685341.285      288693.994
     1685547.044      288237.745
#Sta/Elev= 30
       0 1144.00    36.3 1133.81    49.3 1129.52    75.4 1119.33   140.5 1092.79
   153.5 1086.92   166.5 1080.18   179.6 1075.40   199.4 1070.42   231.7 1065.97
   257.7 1063.80   283.8 1059.15   296.8 1058.40   489.7 1058.19   504.7 1058.16
   517.1 1058.13   570.3 1058.36   583.3 1058.88   589.7 1059.46   609.4 1062.91
   625.6 1064.92   635.4 1067.10   661.5 1076.38   726.6 1106.89   778.2 1128.03
   804.7 1139.67   892.5 1176.40   961.0 1203.03   975.6 1207.47  1001.0 1213.27
#Mann= 3 , 0 , 0
       0     0.1       0   489.7   0.045       0   504.7     0.1       0
Bank Sta=   489.7,   504.7
Exp/Cntr=0.3,0.1

Type RM Length L Ch R = 1 ,3068.3,100.681,102.167,100.68
XS GIS Cut Line= 3
     1685179.516      289167.063     1685385.275      288710.814
     1685591.035      288254.564
#Sta/Elev= 30
       0 1146.91    39.5 1134.07    80.8 1118.63   145.9 1092.52   174.2 1078.93
   185.0 1075.55   198.0 1072.92   250.1 1064.97   290.9 1061.34   323.5 1060.69
   344.7 1058.57   379.6 1058.81   398.6 1057.71   410.1 1058.15   425.5 1057.24
   439.0 1057.67   461.4 1056.62   467.8 1057.19   496.4 1056.58   511.4 1052.30
   523.6 1051.68   549.7 1056.63   578.1 1059.61   588.7 1062.45   614.8 1064.42
   631.9 1068.49   732.0 1108.97   927.4 1193.70   966.4 1208.79  1001.0 1220.69
#Mann= 3 , 0 , 0
       0     0.1       0   496.4   0.045       0   511.4     0.1       0
Bank Sta=   496.4,   511.4
Exp/Cntr=0.3,0.1

Type RM Length L Ch R = 1 ,2966.1,402.705,400,399.358
XS GIS Cut Line= 3
     1685239.079      289193.103     1685475.815      288750.545
     1685658.212      288271.966
#Sta/Elev= 30
       0 1148.23    32.3 1137.12    72.7 1121.89   127.9 1102.60   166.9 1087.78
   180.8 1083.44   247.7 1065.62   261.2 1062.74   277.0 1061.44   285.8 1059.82
   328.5 1047.72   342.0 1045.77   422.7 1039.48   457.7 1037.97   490.1 1037.47
   494.4 1037.48   509.4 1037.60   523.7 1038.45   541.6 1040.62   554.3 1043.41
   576.7 1050.28   592.4 1054.02   605.1 1058.02   655.9 1076.88   743.4 1112.34
   821.1 1145.55   846.5 1157.09   897.3 1181.28   948.1 1204.54  1014.1 1233.46
#Mann= 3 , 0 , 0
       0     0.1       0   494.4   0.045       0   509.4     0.1       0
Bank Sta=   494.4,   509.4
Exp/Cntr=0.3,0.1

Type RM Length L Ch R = 1 ,2566.1,407.087,400,392.764
XS GIS Cut Line= 3
     1685641.097      289367.920     1685788.817      288922.231
     1685963.440      288406.322
#Sta/Elev= 30
       0 1104.64    23.0 1101.73    79.3 1091.92   114.1 1087.77   126.6 1085.05
   154.5 1075.50   164.1 1072.83   173.3 1070.93   214.1 1066.15   226.7 1063.50
   276.3 1048.94   289.2 1047.63   314.1 1050.42   342.4 1050.37   439.3 1042.23
     462 1036.18   464.3 1035.50   473.9 1035.36     477 1035.47   501.9 1042.38
   514.4 1044.40   558.1 1046.63   576.9 1049.38   740.0 1094.57   765.1 1103.35
   852.9 1138.20   890.5 1154.36   932.7 1174.94   960.8 1187.88  1014.2 1207.75
#Mann= 3 , 0 , 0
       0     0.1       0     462   0.045       0     477     0.1       0
Bank Sta=     462,     477
Exp/Cntr=0.3,0.1

Type RM Length L Ch R = 1 ,2166.1,794.982,800,802.676
XS GIS Cut Line= 3
     1686184.114      289412.575     1686188.360      288912.093
     1686192.605      288411.610
#Sta/Elev= 30
       0 1111.55    81.7 1087.19   141.1 1072.36   171.2 1064.10   188.6 1060.75
   224.2 1056.05   236.1 1057.92   259.8 1064.36   271.7 1065.77   354.8 1065.44
   366.7 1063.92   378.5 1060.93   437.9 1042.35   473.5 1036.88   485.4 1033.37
     493 1031.98   497.3 1031.19     508 1033.31   521.0 1040.59   532.9 1048.84
   544.8 1054.45   556.6 1056.97   627.9 1065.38   651.6 1067.30   687.2 1068.24
   699.1 1069.59   711.0 1071.97   817.8 1102.92   889.7 1125.33  1001.0 1168.96
#Mann= 3 , 0 , 0
       0     0.1       0     493   0.045       0     508     0.1       0
Bank Sta=     493,     508
Exp/Cntr=0.3,0.1

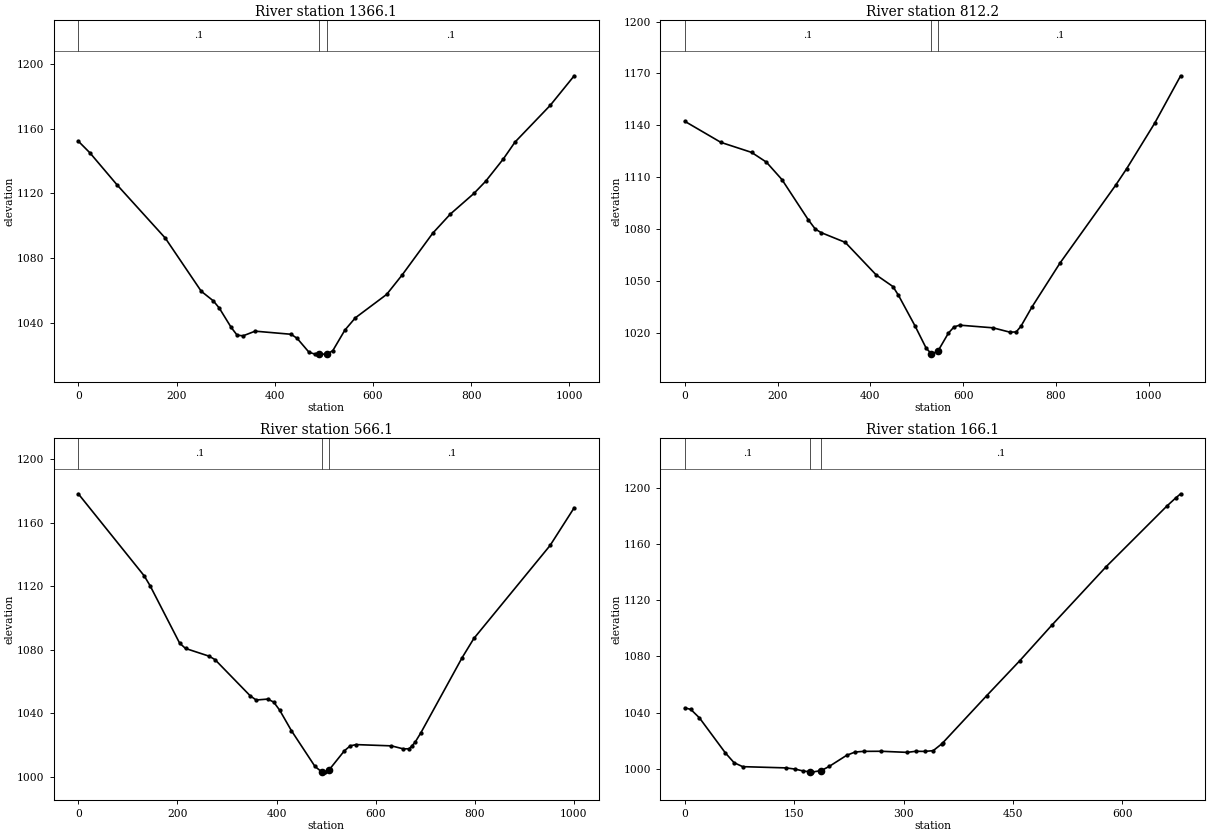
Type RM Length L Ch R = 1 ,1366.1,557.334,553.913,553.74
XS GIS Cut Line= 3
     1686867.123      289420.261     1686980.302      288934.862
     1687044.742      288427.824
#Sta/Elev= 30
       0 1152.23    23.4 1145.08    79.6 1124.93   177.1 1092.23   250.3 1059.33
   274.7 1053.44   286.9 1048.97   311.2 1036.96   323.4 1032.12   335.6 1031.79
   360.0 1034.64   433.1 1032.72   445.3 1030.26   469.7 1021.57   481.9 1020.43
   490.9 1020.43   505.9 1020.43   518.1 1022.59   542.7 1035.31   563.9 1042.87
   627.7 1057.38   659.5 1069.51   721.6 1095.29   757.5 1107.14   805.4 1119.88
   829.3 1127.42   865.2 1141.20   889.1 1151.69   960.9 1174.45  1009.5 1192.69
#Mann= 3 , 0 , 0
       0     0.1       0   490.9   0.045       0   505.9     0.1       0
Bank Sta=   490.9,   505.9
Exp/Cntr=0.3,0.1

Type RM Length L Ch R = 1 ,812.2,248.677,246.087,243.343
XS GIS Cut Line= 3
     1687330.340      289657.414     1687398.899      289111.638
     1687478.012      288598.701
#Sta/Elev= 30
       0 1142.36    77.8 1130.20   144.0 1124.41   175.9 1118.79   209.5 1108.70
   266.3 1085.46   281.3 1080.15   293.7 1078.11   346.0 1072.44   412.9 1053.58
   448.8 1046.92   460.7 1041.87   496.6 1024.09   520.6 1011.25   531.2 1008.24
   532.5 1007.89   546.2 1009.82   568.5 1020.07   580.5 1023.60   592.5 1024.63
   664.6 1023.08   700.7 1020.59   714.5 1020.70   724.7 1023.94   748.7 1035.18
   808.8 1060.41   928.9 1105.41   952.9 1115.06  1013.0 1141.19  1069.1 1168.63
#Mann= 3 , 0 , 0
       0     0.1       0   531.2   0.045       0   546.2     0.1       0
Bank Sta=   531.2,   546.2
Exp/Cntr=0.3,0.1

Type RM Length L Ch R = 1 ,566.1,399.736,400,399.843
XS GIS Cut Line= 3
     1687637.870      289630.266     1687642.963      289131.639
     1687651.600      288629.845
#Sta/Elev= 30
       0 1178.29   132.9 1126.58   144.9 1120.29   204.4 1084.14   216.3 1080.79
   263.8 1075.92   275.7 1073.77   346.9 1050.90   358.8 1048.27   382.5 1048.87
   394.4 1046.91   406.3 1041.85   430.0 1028.93   477.5 1006.39   491.2 1002.93
   497.8 1002.80   506.2 1004.29   536.9 1016.27   548.8 1019.38   560.6 1020.16
   631.9 1019.36   655.6 1017.47   667.5 1017.53   672.9 1019.31   679.4 1021.57
   691.3 1027.67   774.4 1074.96   798.1 1087.08   951.9 1145.72  1000.5 1169.48
#Mann= 3 , 0 , 0
       0     0.1       0   491.2   0.045       0   506.2     0.1       0
Bank Sta=   491.2,   506.2
Exp/Cntr=0.3,0.1

Type RM Length L Ch R = 1 ,166.1,166.41,166.147,166.147
XS GIS Cut Line= 3
     1688039.003      289315.301     1688042.942      289135.724
     1688048.054      288635.250
#Sta/Elev= 30
       0 1043.48     8.2 1042.38    20.1 1036.35    55.7 1011.40    67.6 1004.47
    79.4 1001.66   138.8 1000.78   150.7  999.97   161.9  998.65   172.1  997.92
   174.1  997.77   187.1  998.86   198.1 1001.84   221.9 1009.69   233.5 1012.06
   245.3 1012.54   269.4 1012.60   305.0 1011.82   316.9 1012.59   328.8 1012.50
   340.7 1013.03   352.5 1017.88   354.1 1018.74   414.0 1052.10   459.4 1076.95
   503.8 1102.47   578.1 1143.95   661.2 1186.97   673.1 1192.62   680.1 1195.68
#Mann= 3 , 0 , 0
       0     0.1       0   172.1   0.045       0   187.1     0.1       0
Bank Sta=   172.1,   187.1
Exp/Cntr=0.3,0.1